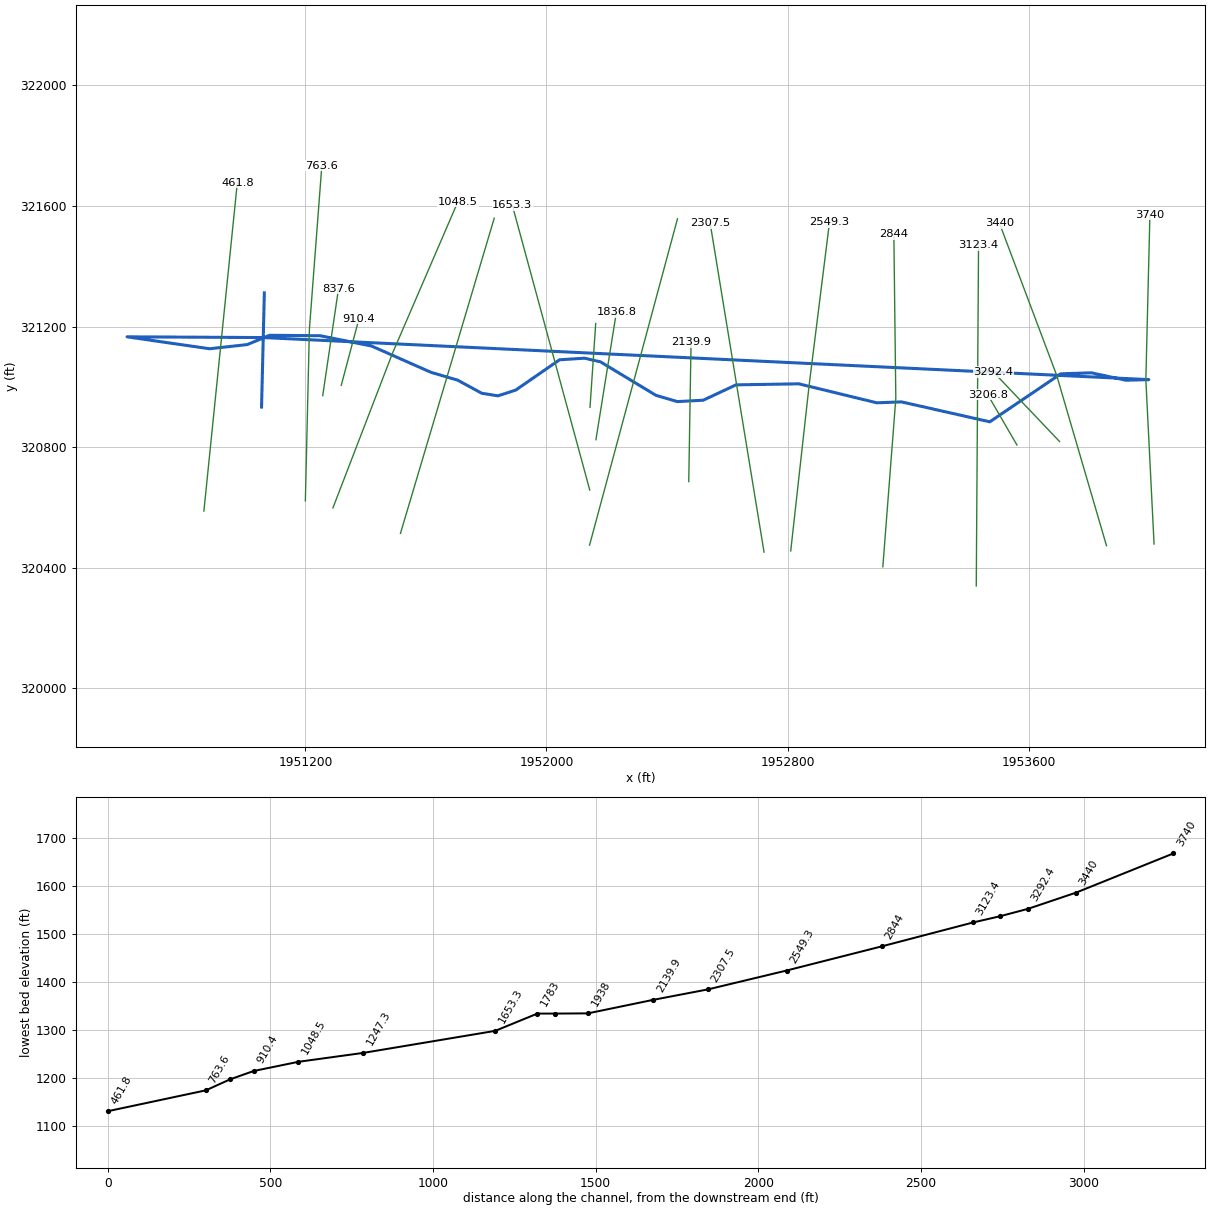
--- NP16.prj (project) ---

Proj Title=NP16
Current Plan=p01
Default Exp/Contr=0,0
English Units
Geom File=g01
Flow File=f01
Plan File=p01
BEGIN DESCRIPTION:
END DESCRIPTION:
DSS Export Rating Curves= 0
DSS Export Rating Curve Sorted= 0
DSS Export Volume Flow Curves= 0
DXF OffsetX= 0
DXF OffsetY= 0
DXF ScaleX= 0
DXF ScaleY= 0

--- NP16.p01 (plan) ---

Plan Title=Floodplain
Program Version=4.00
Geom File=g01
Flow File=f01
K Sum by GR=0
Std Step Tol=0.01
Critical Tol=0.01
Num of Std Step Trials=20
Max Error Tol=0.3
Flow Tol Ratio=0.001
Split Flow NTrial=30
Split Flow Tol=0.02
Split Flow Ratio=0.02
Log Output Level=0
Friction Slope Method=1
Unsteady Friction Slope Method=2
Unsteady Bridges Friction Slope Method=1
Global Log Level=0
CheckData=False
Run HTab=0
Run UNet=0
Run PostProcess=0
UNET Theta=0
UNET Theta Warmup=0
UNET ZTol=0
UNET ZSATol=0
UNET MxIter=0
UNET MaxInSteps=0
UNET DtIC=0
UNET DtMin=0
UNET MaxCRTS=0
UNET WFStab=0
UNET SFStab=0
UNET WFX=0
UNET SFX=0
UNET DSS MLevel=0
UNET DZMax Abort=0
UNET Convert EG Bridges=0
UNET Use Existing IB Tables=0
UNET Froude Limit=0
UNET Froude Power=0
Write IC File=0
Echo Input=False
Echo Output=False
Write Detailed=0

--- NP16.f01 (steady flow) ---

Flow Title=NFF Regression Equation
Program Version=4.00
Number of Profiles=1
Profile Names=P100yr
River Rch & RM=NP16,Main      ,3740
540.2897
River Rch & RM=NP16,Main      ,2844
572.3999
Boundary for River Rch & Prof#=NP16,Main      ,1
Up Type=0
Dn Type=3
Dn Slope=0.229977

--- NP16.g01 (geometry) ---

Geom Title=USGS 3m DEM
Program Version=4.10

River Reach=NP16            ,Main
Reach XY= 30
     1951054.627       320932.93      1951060.28      321163.423
     1953998.618      321023.842     1953922.477      321021.858
     1953807.646      321046.411     1953706.561      321043.122
      1953470.81      320883.905     1953178.056      320949.979
     1953095.881      320946.962      1952837.16      321009.953
     1952628.826      321006.481     1952519.988      320955.534
     1952434.382      320950.925     1952363.201      320971.758
     1952179.173       321082.87     1952125.986      321095.022
     1952043.336      321089.647     1951897.924       320989.12
     1951838.896      320970.022     1951785.076      320978.703
     1951705.215      321022.106     1951616.673      321048.147
     1951419.846      321135.241     1951248.862      321169.468
     1951081.493         321171.     1951007.298      321140.161
     1950882.299      321126.273     1950608.277      321165.871
      1951060.28      321163.423     1951063.913      321311.597

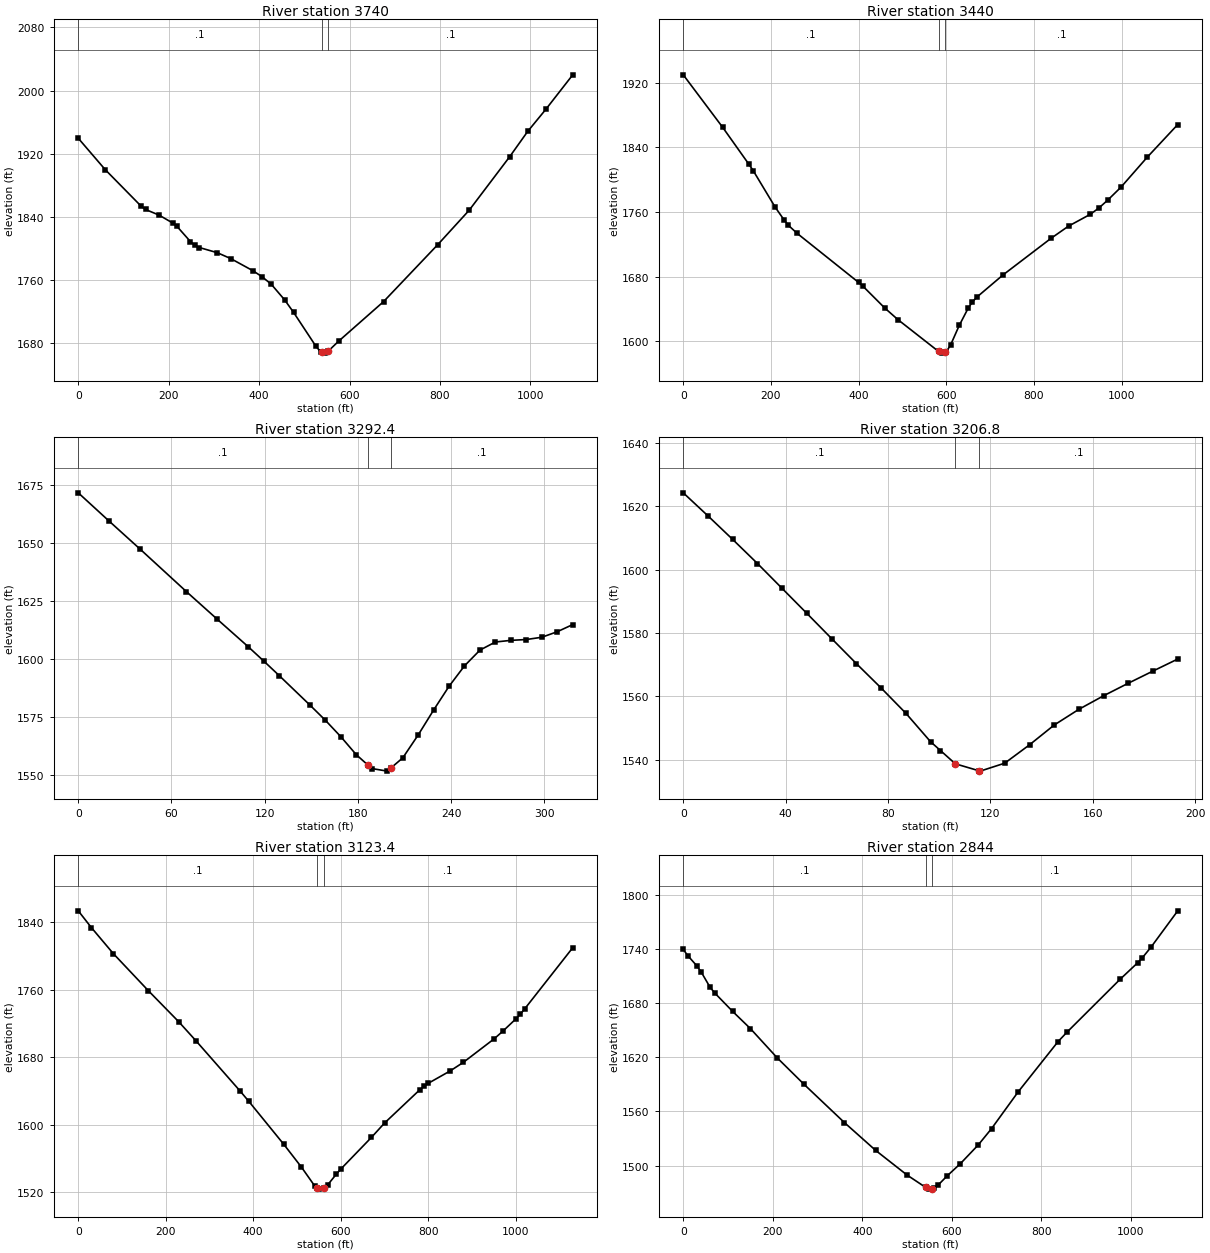
Type RM Length L Ch R = 1 ,3740    ,294.5,299.7,308.4
XS GIS Cut Line= 3
     1954015.882      320478.349      1953988.63      321023.343
     1954002.096      321571.023
#Sta/Elev= 30
       0 1939.45    59.5 1899.72   138.9 1853.38   148.8 1849.11   178.6 1842.04
   208.4 1832.13   218.3 1827.69     248 1808.46     258 1803.48   267.9 1800.86
   307.6 1794.29   337.3 1786.82   386.9 1771.26   406.8 1763.66   426.6 1754.44
   456.4 1734.47   476.2 1718.59   525.8 1675.43   535.8 1668.74   538.2 1668.31
   545.7 1666.96   553.2  1669.7   575.6 1682.03   675.2 1732.33   794.7 1804.36
   864.4 1848.14   954.1 1916.11   993.9 1948.17  1033.8 1976.02  1093.5  2019.9
#Mann= 3 , 0 , 0
       0      .1       0   538.2    .045       0   553.2      .1       0
Bank Sta=538.2,553.2
XS Rating Curve= 0 ,0
Exp/Cntr=0.3,0.1

Type RM Length L Ch R = 1 ,3440    ,136.6,147.4,156.6
XS GIS Cut Line= 3
     1953858.049      320472.974     1953692.531      321038.852
     1953502.976      321542.488
#Sta/Elev= 30
       0 1929.91    89.9 1864.89   149.9 1819.02   159.9 1810.93   209.8 1765.91
   229.8 1750.36   239.8 1743.55   259.8  1733.6   399.7 1672.96   409.7 1668.25
   459.7 1641.12   489.7 1626.77   582.1  1587.5   589.6 1585.36   597.1 1586.49
   599.6 1586.87   609.5 1595.27   629.4 1619.67   649.4 1640.62   659.4  1648.7
   669.3 1654.58   729.1 1682.13   838.7 1727.49   878.6  1742.6   928.4 1757.26
   948.3 1765.24   968.3 1774.93   998.2 1790.82    1058 1827.86  1127.7 1868.37
#Mann= 3 , 0 , 0
       0      .1       0   582.1    .045       0   597.1      .1       0
Bank Sta=582.1,597.1
XS Rating Curve= 0 ,0
Exp/Cntr=0.3,0.1

Type RM Length L Ch R = 1 ,3292.4  ,90.8,85.4,80
XS GIS Cut Line= 2
     1953702.454      320818.266     1953483.205      321048.968
#Sta/Elev= 28
       0 1671.77    19.9 1659.55    39.8 1647.49    69.6 1629.17    89.5 1617.22
   109.4 1605.39   119.4 1599.22   129.3 1592.97   149.2 1580.18   159.1 1573.65
   169.1 1566.52     179 1558.79   186.3 1554.45     189 1552.85   198.9 1551.74
   201.3 1553.12   208.9 1557.47   218.8 1567.34   228.8 1578.15   238.7 1588.36
   248.6 1597.14   258.6 1603.95   268.5 1607.43   278.5 1608.14   288.4  1608.5
   298.4 1609.48   308.3 1611.86   318.3 1614.95
#Mann= 3 , 0 , 0
       0      .1       0   186.3    .045       0   201.3      .1       0
Bank Sta=186.3,201.3
XS Rating Curve= 0 ,0
Exp/Cntr=0.3,0.1

Type RM Length L Ch R = 1 ,3206.8  ,95,83.5,71.9
XS GIS Cut Line= 2
     1953560.846      320807.052     1953463.858      320974.202
#Sta/Elev= 23
       0 1624.25     9.7 1616.94    19.3 1609.55      29 1601.94    38.6 1594.11
    48.3  1586.2      58 1578.23    67.6 1570.39    77.3 1562.67      87 1554.67
    96.6 1545.73   100.5 1542.92   106.3 1538.74   115.5 1536.55     116 1536.43
   125.6 1538.94   135.3 1544.74   144.9 1550.96   154.6 1555.95   164.3 1560.24
   173.9 1564.18   183.6 1568.04   193.2  1571.8
#Mann= 3 , 0 , 0
       0      .1       0   106.3    .045       0   115.5      .1       0
Bank Sta=106.3,115.5
XS Rating Curve= 0 ,0
Exp/Cntr=0.3,0.1

Type RM Length L Ch R = 1 ,3123.4  ,281.3,279.3,278.4
XS GIS Cut Line= 2
     1953425.971      320339.493     1953433.539      321470.016
#Sta/Elev= 30
       0 1853.59      30 1833.69      80 1802.92   160.1 1758.91   230.1 1721.76
   270.1 1698.82   370.2 1639.69   390.2 1627.38   470.2 1576.36   510.2 1549.56
   540.3 1527.38   546.2 1525.03   550.3  1523.4   561.2 1524.39   570.3 1528.46
   590.3 1541.32   600.3 1547.21   670.3 1584.78   700.3 1601.82   780.4 1641.05
   790.4 1645.42   800.4 1649.01   850.4 1663.66   880.4 1673.79   950.5 1701.56
   970.5 1710.66  1000.5 1725.34  1010.5 1730.88  1020.5 1737.12  1130.6 1809.84
#Mann= 3 , 0 , 0
       0      .1       0   546.2    .045       0   561.2      .1       0
Bank Sta=546.2,561.2
XS Rating Curve= 0 ,0
Exp/Cntr=0.3,0.1

Type RM Length L Ch R = 1 ,2844    ,294.3,293.7,291.8
XS GIS Cut Line= 3
     1953115.975      320402.761     1953159.046      320960.985
     1953152.559      321505.783
#Sta/Elev= 30
       0 1739.31      10 1732.54      30 1721.33      40  1714.4      60 1697.35
      70 1691.28     110 1670.87     150 1651.69     210 1619.24   269.9 1589.96
   359.9 1547.69   429.9  1516.8   499.9 1489.58   541.8 1475.79   549.9 1473.96
   556.8 1474.44   559.9 1474.66   569.8 1478.69   589.6 1488.65   619.3 1502.26
   658.9 1522.83   688.7 1540.95   748.1 1581.59   837.2 1637.24   857.1 1647.66
   975.9 1706.29  1015.6 1724.77  1025.5 1730.05  1045.3 1742.08  1104.7 1782.08
#Mann= 3 , 0 , 0
       0      .1       0   541.8    .045       0   556.8      .1       0
Bank Sta=541.8,556.8
XS Rating Curve= 0 ,0
Exp/Cntr=0.3,0.1

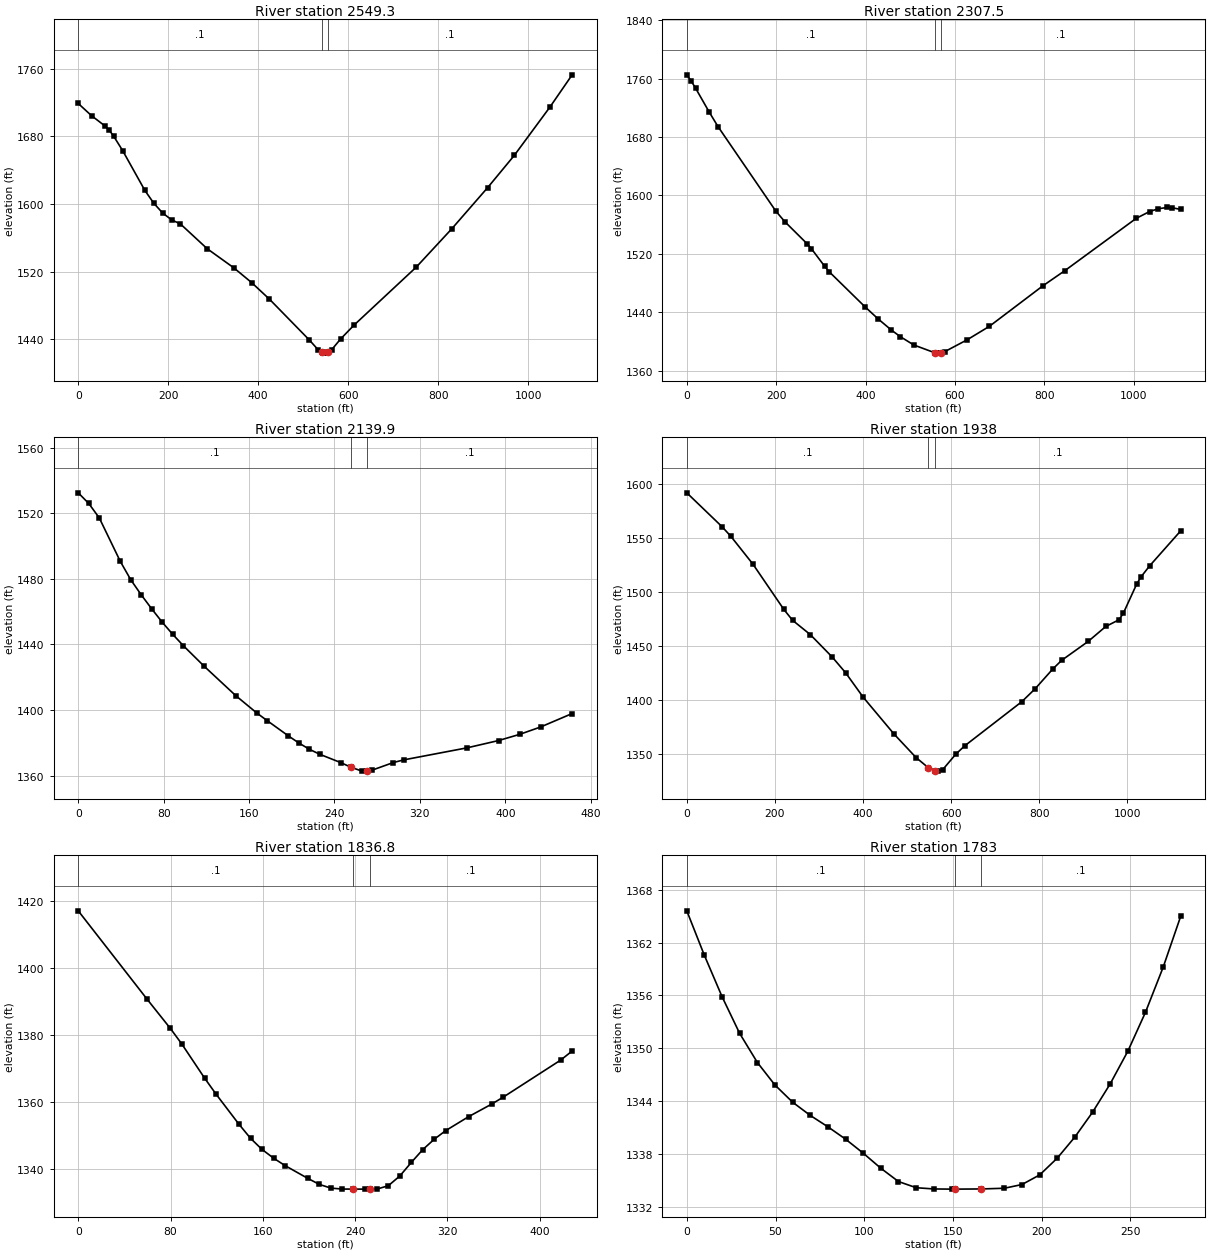
Type RM Length L Ch R = 1 ,2549.3  ,235.7,241.8,248.1
XS GIS Cut Line= 3
     1952810.367      320455.586     1952871.498      321005.661
     1952939.058      321546.138
#Sta/Elev= 30
       0 1718.96    29.6 1704.49    59.3  1692.4    69.2 1687.14    79.1 1679.97
    98.8 1663.13   148.2 1616.02     168 1600.91   187.8 1589.27   207.6 1581.27
   227.3 1576.34   286.6 1547.14   345.9 1524.46   385.4 1507.05     425 1487.44
   513.9 1439.02   533.7 1427.31   540.9 1424.57   543.6 1423.54   553.5 1423.57
   555.9 1424.54   563.4 1427.57   583.2 1440.21   612.9 1456.54   751.5 1525.31
   830.8 1570.85     910 1619.25   969.4 1657.47  1048.6 1714.64  1098.1 1752.86
#Mann= 3 , 0 , 0
       0      .1       0   540.9    .045       0   555.9      .1       0
Bank Sta=540.9,555.9
XS Rating Curve= 0 ,0
Exp/Cntr=0.3,0.1

Type RM Length L Ch R = 1 ,2307.5  ,171.5,167.4,163.4
XS GIS Cut Line= 2
     1952721.832      320451.484     1952543.123      321542.345
#Sta/Elev= 30
       0 1765.09      10 1756.43    19.9 1746.57    49.8 1714.49    69.7 1694.38
   199.2 1578.67   219.1 1564.35   268.9 1534.13   278.8 1527.24   308.7 1502.96
   318.7 1495.63   398.3 1447.99   428.2 1431.12   458.1 1415.75     478 1406.79
   507.9  1395.5   554.9 1384.83   567.6 1384.32   569.9 1384.81   577.6 1386.44
   627.4 1402.56   677.2    1421   796.7 1476.31   846.5 1497.35  1005.8 1568.71
  1035.7 1578.04  1055.6 1581.93  1075.5  1583.6  1085.5 1583.33  1105.4 1580.92
#Mann= 3 , 0 , 0
       0      .1       0   554.9    .045       0   569.9      .1       0
Bank Sta=554.9,569.9
XS Rating Curve= 0 ,0
Exp/Cntr=0.3,0.1

Type RM Length L Ch R = 1 ,2139.9  ,207.2,201.7,196.2
XS GIS Cut Line= 2
     1952472.042      320685.462     1952479.677      321147.957
#Sta/Elev= 30
       0 1532.47     9.8 1526.02    19.7 1517.18    39.4 1490.64    49.2 1479.43
      59 1470.25    68.9 1461.61    78.7 1453.52    88.6 1446.06    98.4 1439.25
   118.1 1426.58   147.6 1408.71   167.3 1398.13   177.2 1393.39   196.8  1384.2
   206.7 1379.84   216.5 1376.02   226.4 1372.93     246 1367.86   255.3 1365.12
   265.7  1362.7   270.3 1363.02   275.6 1363.38   295.2 1367.96   305.1 1369.59
   364.1  1376.9   393.7 1381.36   413.4 1385.12     433 1389.61   462.6 1397.83
#Mann= 3 , 0 , 0
       0      .1       0   255.3    .045       0   270.3      .1       0
Bank Sta=255.3,270.3
XS Rating Curve= 0 ,0
Exp/Cntr=0.3,0.1

Type RM Length L Ch R = 1 ,1938    ,98.3,101.2,104.1
XS GIS Cut Line= 2
     1952142.929      320474.785      1952434.63      321557.562
#Sta/Elev= 30
       0 1591.65    80.1 1560.31   100.1 1551.42   150.2 1525.72   220.3 1483.91
   240.3 1473.81   280.4 1460.64   330.4 1439.81   360.4 1425.46   400.5 1402.77
   470.6 1368.71   520.6    1347   548.4 1337.62   563.4 1334.93   570.7 1334.49
   580.7  1335.7   610.8  1350.2   630.8 1357.81   760.9 1398.75     791 1410.65
     831 1428.89     851 1436.84   911.1  1454.3   951.2 1468.14   981.2 1474.34
   991.2 1480.47  1021.3 1507.22  1031.3 1514.03  1051.3 1524.39  1121.4 1556.54
#Mann= 3 , 0 , 0
       0      .1       0   548.4    .045       0   563.4      .1       0
Bank Sta=548.4,563.4
XS Rating Curve= 0 ,0
Exp/Cntr=0.3,0.1

Type RM Length L Ch R = 1 ,1836.8  ,52.3,53.9,55.3
XS GIS Cut Line= 2
     1952164.045      320824.508     1952231.916       321247.25
#Sta/Elev= 30
       0 1417.08    59.7 1390.71    79.7 1382.07    89.6 1377.45   109.5  1367.2
   119.5 1362.38   139.4 1353.39   149.4 1349.21   159.3 1345.91   169.3 1343.31
   179.2  1341.1   199.1 1337.25   209.1 1335.46   219.1 1334.36     229 1334.08
   238.1 1334.07   248.9 1334.06   253.1 1334.06   258.9 1334.07   268.8 1335.07
   278.8 1337.98   288.8 1342.04   298.7 1345.85   308.7 1348.96   318.6 1351.52
   338.5 1355.69   358.5 1359.44   368.4 1361.49   418.2 1372.54   428.2 1375.26
#Mann= 3 , 0 , 0
       0      .1       0   238.1    .045       0   253.1      .1       0
Bank Sta=238.1,253.1
XS Rating Curve= 0 ,0
Exp/Cntr=0.3,0.1

Type RM Length L Ch R = 1 ,1783    ,122.4,129.8,137.3
XS GIS Cut Line= 2
     1952144.441      320932.223     1952163.348      321210.011
#Sta/Elev= 29
       0 1365.59     9.9 1360.55    19.9 1355.85    29.8  1351.7    39.8  1348.4
    49.7 1345.85    59.7  1343.9    69.6 1342.41    79.6 1341.11    89.5 1339.72
    99.4 1338.14   109.4 1336.42   119.3 1334.92   129.3 1334.22   139.2 1334.08
   149.2 1334.06   151.1 1334.06   166.1 1334.08     179 1334.16   188.9 1334.58
   198.9 1335.67   208.8 1337.57   218.8 1339.98   228.7 1342.77   238.6 1345.97
   248.6 1349.69   258.5 1354.08   268.5  1359.2   278.4 1364.98
#Mann= 3 , 0 , 0
       0      .1       0   151.1    .045       0   166.1      .1       0
Bank Sta=151.1,166.1
XS Rating Curve= 0 ,0
Exp/Cntr=0.3,0.1

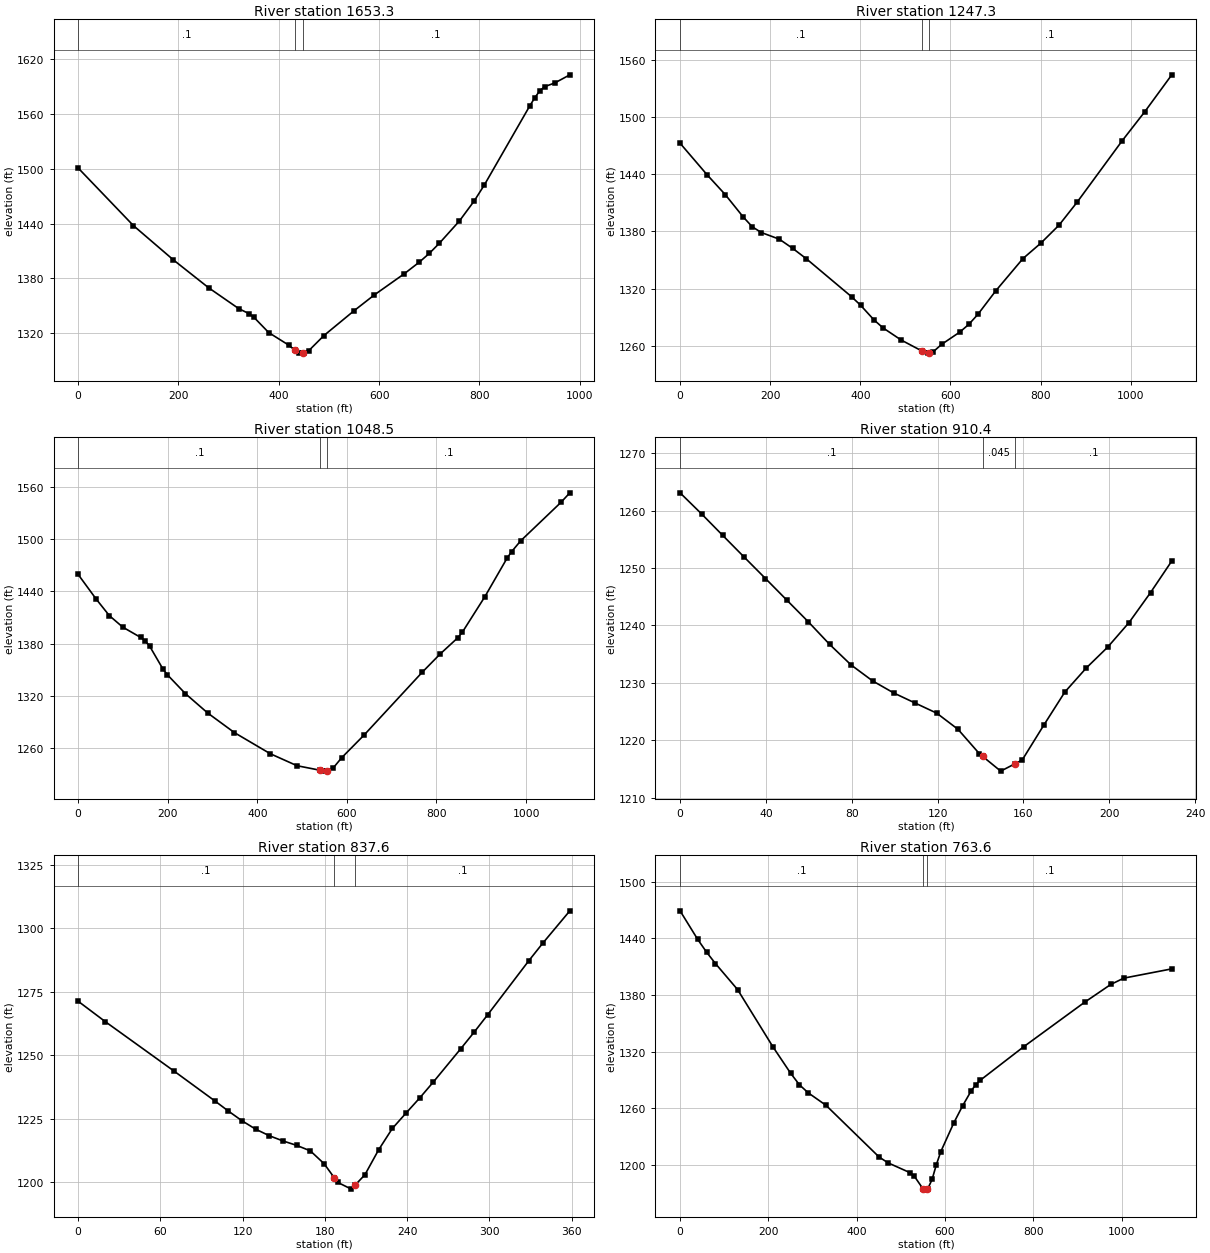
Type RM Length L Ch R = 1 ,1653.3  ,418.5,405.8,393.2
XS GIS Cut Line= 2
     1952143.562      320657.617     1951886.372      321603.325
#Sta/Elev= 30
       0 1500.89     110 1437.88     190 1400.16     260 1369.74     320 1346.89
     340  1341.5     350 1337.57     380 1320.56     420  1306.8   432.5 1300.99
     440 1298.54   447.5 1298.21     450  1298.1     460 1300.94     490 1317.37
     550 1344.52     590 1361.68     650 1384.99     680 1397.73     700 1407.35
     720 1418.42     760 1442.85     790 1465.19     810 1482.57     900 1568.66
     910 1577.64     920 1585.27     930 1589.98   950.1 1594.03   980.1 1602.92
#Mann= 3 , 0 , 0
       0      .1       0   432.5    .045       0   447.5      .1       0
Bank Sta=432.5,447.5
XS Rating Curve= 0 ,0
Exp/Cntr=0.3,0.1

Type RM Length L Ch R = 1 ,1247.3  ,200.6,198.8,196.1
XS GIS Cut Line= 2
     1951515.498      320513.711     1951826.627      321559.458
#Sta/Elev= 30
       0 1472.45    60.1 1439.29   100.1 1418.66   140.1 1395.13   160.2 1384.81
   180.2  1378.8   220.2 1371.82   250.2 1362.06   280.3 1351.23   380.4  1311.5
   400.4 1302.58   430.4 1287.07   450.4 1278.75   490.5 1266.06   536.6 1254.54
   550.5 1252.29   551.6 1252.39   560.5 1253.23   580.6 1261.56   620.6 1274.34
   640.6 1282.43   660.6 1292.82   700.7 1317.76   760.7 1351.41   800.8 1367.78
   840.8 1386.49   880.8 1410.49   980.9    1475    1031 1505.42    1091 1544.19
#Mann= 3 , 0 , 0
       0      .1       0   536.6    .045       0   551.6      .1       0
Bank Sta=536.6,551.6
XS Rating Curve= 0 ,0
Exp/Cntr=0.3,0.1

Type RM Length L Ch R = 1 ,1048.5  ,135.5,138,141.4
XS GIS Cut Line= 3
      1951291.52      320598.354     1951488.628      321110.307
     1951706.195      321614.534
#Sta/Elev= 30
       0 1459.26    39.9 1431.26    69.8 1411.98    99.7 1398.84   139.6 1387.06
   149.6 1383.13   159.6 1377.11   189.5 1350.72   199.5 1344.11   239.4 1322.69
   289.2 1300.47   349.1 1277.91   428.9  1253.8   488.7 1240.03   541.1 1234.75
   548.6 1233.83   556.1 1233.88   568.6  1236.9   588.5 1249.24   638.4 1275.15
   768.2 1347.14   808.2 1368.03   848.1 1386.88   858.1 1393.27     908 1433.64
     958  1478.2     968 1485.47   987.9 1497.67  1077.8 1541.74  1097.8 1552.77
#Mann= 3 , 0 , 0
       0      .1       0   541.1    .045       0   556.1      .1       0
Bank Sta=541.1,556.1
XS Rating Curve= 0 ,0
Exp/Cntr=0.3,0.1

Type RM Length L Ch R = 1 ,910.4   ,70.1,72.6,75.2
XS GIS Cut Line= 2
     1951319.076      321004.943     1951377.978      321226.373
#Sta/Elev= 26
       0 1263.09      10 1259.43    19.9 1255.67    29.9 1251.89    39.8 1248.17
    49.8 1244.39    59.8 1240.62    69.7  1236.7    79.7 1233.12    89.7 1230.35
    99.6 1228.24   109.6 1226.48   119.6 1224.73   129.5 1221.92   139.5 1217.66
     141  1217.2   149.4 1214.64     156 1215.91   159.4 1216.57   169.4  1222.6
   179.3 1228.42   189.3 1232.61   199.2 1236.21   209.2 1240.51   219.2 1245.72
   229.1 1251.22
#Mann= 3 , 0 , 0
       0      .1       0     141    .045       0     156      .1       0
Bank Sta=141,156
XS Rating Curve= 0 ,0
Exp/Cntr=0.3,0.1

Type RM Length L Ch R = 1 ,837.6   ,71.2,74.1,76.8
XS GIS Cut Line= 2
     1951257.597      320970.552     1951309.955      321325.423
#Sta/Elev= 28
       0 1271.28    19.9  1263.2    69.8 1243.81    99.6 1232.04   109.6 1227.99
   119.6 1224.14   129.5 1220.85   139.5 1218.26   149.5  1216.2   159.4 1214.47
   169.4  1212.3   179.4 1207.26   186.8 1201.76   189.3  1199.9   199.3 1197.22
   201.8 1198.65   209.2 1202.88   219.2  1212.7   229.2 1221.12   239.1 1227.13
   249.1  1233.1   259.1 1239.42     279 1252.47     289 1259.16   298.9 1266.04
   328.8 1287.26   338.8 1294.05   358.7 1306.91
#Mann= 3 , 0 , 0
       0      .1       0   186.8    .045       0   201.8      .1       0
Bank Sta=186.8,201.8
XS Rating Curve= 0 ,0
Exp/Cntr=0.3,0.1

Type RM Length L Ch R = 1 ,763.6   ,303.6,301.8,300.1
XS GIS Cut Line= 3
     1951199.989      320621.465     1951213.428      321191.971
     1951254.629      321733.231
#Sta/Elev= 30
       0 1469.09      40 1438.83    60.1  1425.3    80.1 1413.29   130.2 1385.76
   210.2  1325.2   250.3 1297.24   270.3 1284.95   290.3 1276.41   330.4 1263.26
   450.5  1208.6   470.6 1202.42   520.6 1191.93   530.6 1188.11   550.6  1174.5
   558.6 1174.51   560.6 1174.51   570.7 1184.73   580.5 1200.54   590.4 1214.13
     620 1244.72   639.8 1262.65   659.5 1278.71   669.4 1284.89   679.2 1289.53
   777.9 1325.12   916.1  1372.3   975.3 1391.14  1004.9 1397.85  1113.5 1407.65
#Mann= 3 , 0 , 0
       0      .1       0   550.6    .045       0   558.6      .1       0
Bank Sta=550.6,558.6
XS Rating Curve= 0 ,0
Exp/Cntr=0.3,0.1

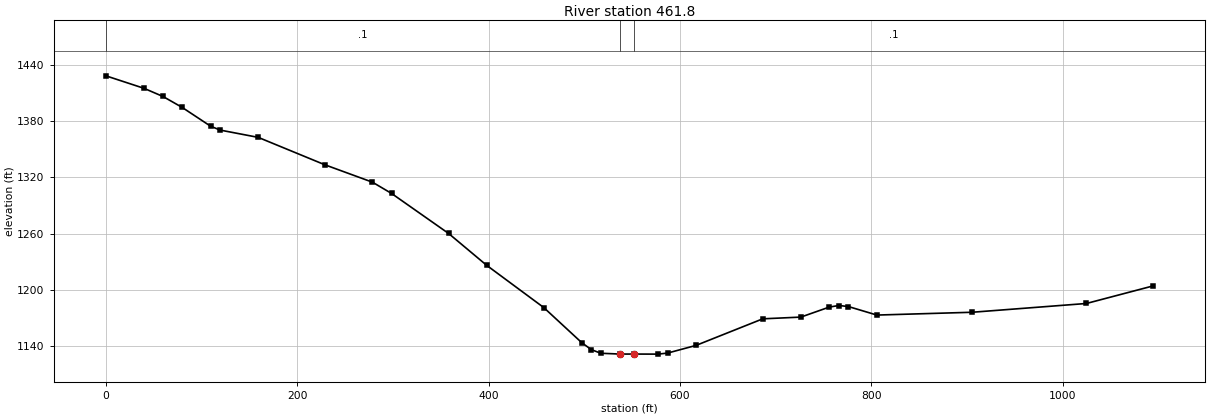
Type RM Length L Ch R = 1 ,461.8   ,313.8,313.5,313.2
XS GIS Cut Line= 2
     1950863.336      320587.804      1950974.18      321676.543
#Sta/Elev= 30
       0 1428.62    39.8 1415.27    59.7 1406.52    79.6 1394.92   109.4 1374.78
   119.4 1370.61   159.2 1362.82   228.8 1333.53   278.6  1314.9   298.5  1302.9
   358.2 1260.06     398 1225.99   457.6 1180.89   497.4 1143.25   507.4 1135.85
   517.3    1132   537.2 1131.16   552.2 1131.16     577 1131.08     587  1132.2
   616.8 1140.42   686.5 1168.82   726.3 1170.67   756.1 1181.41   766.1 1183.06
     776 1181.95   805.8 1172.84   905.3 1175.84  1024.7 1185.22  1094.4    1204
#Mann= 3 , 0 , 0
       0      .1       0   537.2    .045       0   552.2      .1       0
Bank Sta=537.2,552.2
XS Rating Curve= 0 ,0
Exp/Cntr=0.3,0.1

Chan Stop Cuts=-1
Use User Specified Reach Order=0
Composite Channel Slope=5